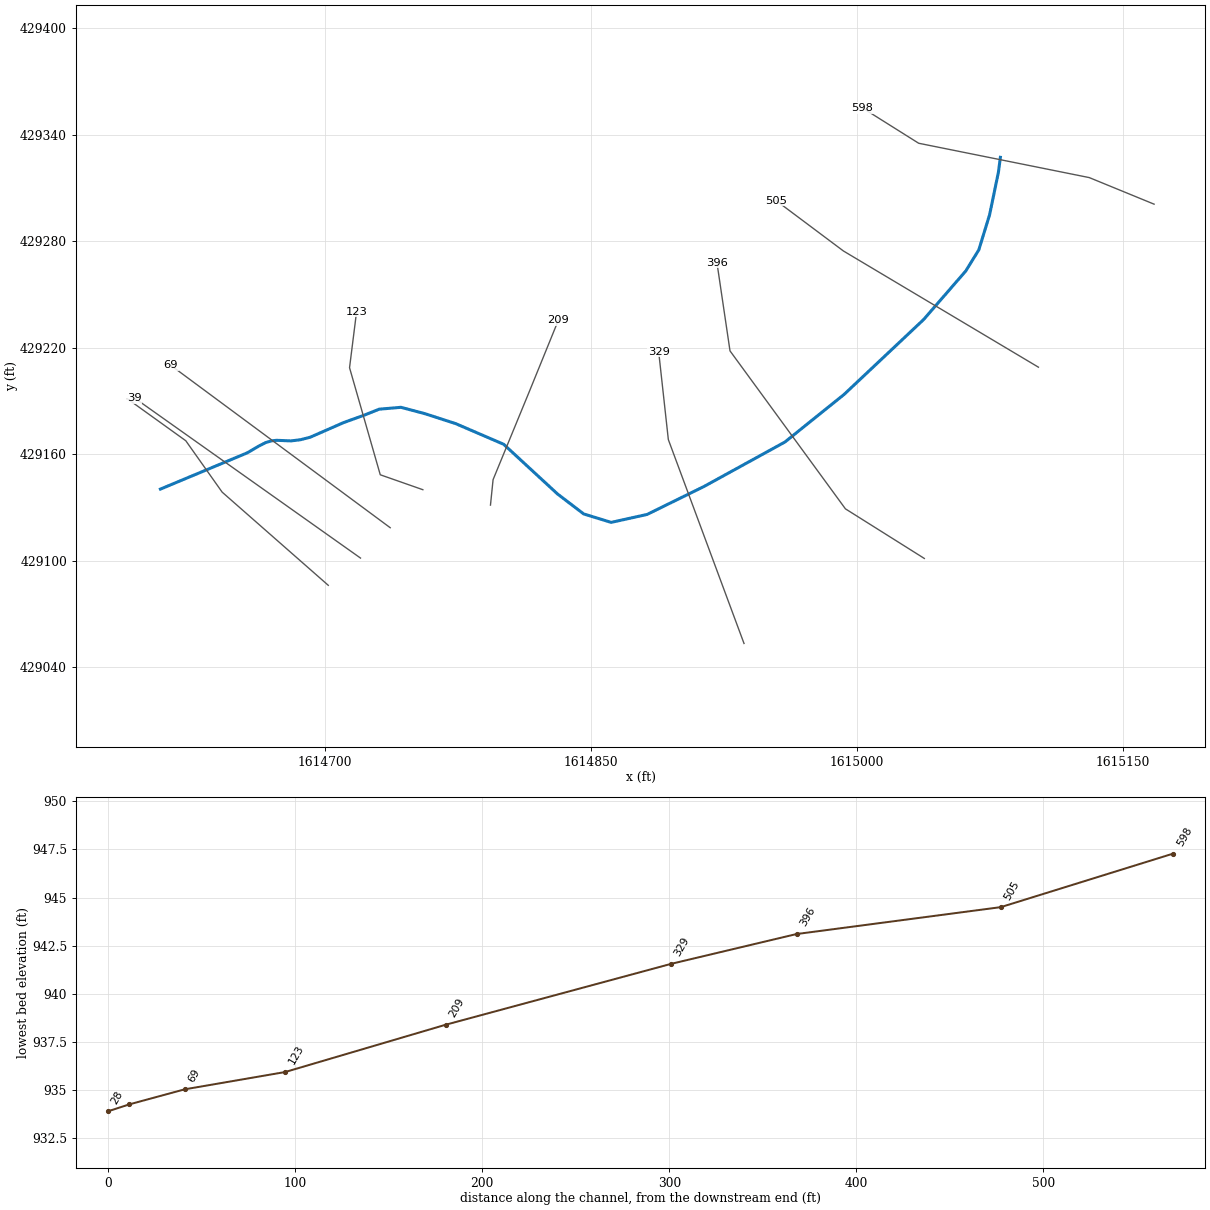
--- FRBEERN.prj (project) ---

Proj Title=FRBEERN
Current Plan=p01
Default Exp/Contr=0.3,0.1
English Units
Geom File=g01
Flow File=f01
Plan File=p01
Y Axis Title=Elevation
X Axis Title(PF)=Main Channel Distance
X Axis Title(XS)=Station
BEGIN DESCRIPTION:
---------- MODELED AS PART OF WVEMD CTP PROGRAM, 2023----------
Stream Name: Furbee Run
Flood Zone:  AFH
Wetzel County, WV
HEC-RAS Version: RAS 6.3
Vertical Datum: NAVD88
Projection: NAD 1983 StatePlane West Virginia S FIPS 4702 (US Feet)
Terrain: 1-meter West Virginia FEMA R3 South Central (collected 2018-2020)
Land Use: 2019 NLCD
Hydrologic Method:
WV SIR2010-5033 regression equations
Additional Model Notes:
None
END DESCRIPTION:
DSS File=dss
DSS Export Rating Curves= 0
DSS Export Rating Curve Sorted= 0
DSS Export Volume Flow Curves= 0
DXF OffsetX= 0
DXF OffsetY= 0
DXF ScaleX= 1
DXF ScaleY= 10

--- FRBEERN.p01 (plan) ---

Plan Title=Floodplain
Program Version=6.30
Short Identifier=Floodplain
Geom File=g01
Flow File=f01
Subcritical Flow
K Sum by GR= 0
Std Step Tol= 0.01
Critical Tol= 0.01
Num of Std Step Trials= 20
Max Error Tol= 0.3
Flow Tol Ratio= 0.001
Split Flow NTrial= 30
Split Flow Tol= 0.02
Split Flow Ratio= 0.02
Log Output Level= 0
Friction Slope Method= 1
Unsteady Friction Slope Method= 2
Unsteady Bridges Friction Slope Method= 1
Parabolic Critical Depth
Global Vel Dist= 0 , 0 , 0
Global Log Level= 0
CheckData=True
Encroach Param=-1 ,0,0, 0
Computation Interval=1MIN
Output Interval=1HOUR
Instantaneous Interval=1HOUR
Mapping Interval=1HOUR
Computation Time Step Use Courant=        0
Computation Time Step Use Time Series=    0
Computation Time Step Count To Double=0
Computation Time Step Max Doubling=0
Computation Time Step Max Halving=0
Computation Time Step Residence Courant=0
Run HTab= 0
Run UNet= 0
Run Sediment= 0
Run PostProcess= 0
Run WQNet= 0
Run RASMapper=-1
UNET Theta= 1
UNET Theta Warmup= 1
UNET ZTol= 0.02
UNET ZSATol= 0.02
UNET MxIter= 20
UNET Max Iter WO Improvement= 0
UNET MaxInSteps= 0
UNET DtIC= 0
UNET DtMin= 0
UNET MaxCRTS= 20
UNET WFStab= 2
UNET SFStab= 1
UNET WFX= 1
UNET SFX= 1
UNET Gravity=32.17405
UNET 1D Methodology=Finite Difference
UNET DSS MLevel= 4
UNET Pardiso=0
UNET DZMax Abort= 100
UNET Use Existing IB Tables=-1
UNET Froude Reduction=False
UNET Froude Limit= 0.8
UNET Froude Power= 4
UNET D1 Cores= 0
UNET WindReference=Eulerian
UNET WindDragFormulation=Hsu (1988)
UNET D2 Coriolis=0
UNET D2 Cores= 0
UNET D2 Theta= 1
UNET D2 Theta Warmup= 1
UNET D2 Z Tol= 0.01
UNET D2 Volume Tol= 0.01
UNET D2 Max Iterations= 20
UNET D2 Equation= 0
UNET D2 RampUpFraction=0.1
UNET D2 TimeSlices= 1
UNET D2 Turbulence Formulation=None
UNET D2 Eddy Viscosity=0.3
UNET D2 Transverse Eddy Viscosity=0.1
UNET D2 Smagorinsky Mixing=0.05
UNET D2 BCVolumeCheck=0
UNET D2 Cores=0
UNET D2 SolverType=PARDISO (Direct)
UNET D2 Minimum Iterations= 3
UNET D2 Maximum Iterations= 30
UNET D2 Restart Number= 10
UNET D2 Relaxation Coeff=1.3
UNET D2 SOR Precondition Iterations= 10
UNET D2 ILUT Maximum Fill= 8
UNET D2 ILUT Tolerance=1E-08
UNET D2 Convergence Tolerance=0.00001
UNET D1D2 MaxIter= 0
UNET D1D2 ZTol=0.01
UNET D1D2 QTol=0.1
UNET D1D2 MinQTol=1
DSS File=dss
Write IC File= 0
Write IC File at Fixed DateTime=0
Write IC File at Sim End=0
Echo Input=False
Echo Parameters=False
Echo Output=False
Write Detailed= 0
HDF Write Warmup=0
HDF Write Time Slices=0
HDF Flush=0
HDF Compression= 1
HDF Chunk Size= 1
HDF Spatial Parts= 1
HDF Use Max Rows=0
HDF Fixed Rows= 1
Calibration Method= 0
Calibration Iterations= 20
Calibration Max Change=0.05
Calibration Tolerance=0.2
Calibration Maximum=1.5
Calibration Minimum=0.5
Calibration Optimization Method= 1
WQ AD Non Conservative
WQ ULTIMATE=-1
WQ Max Comp Step=1HOUR
WQ Output Interval=15MIN
WQ Output Selected Increments= 0
WQ Output face flow=0
WQ Output face velocity=0
WQ Output face area=0
WQ Output face dispersion=0
WQ Output cell volume=0
WQ Output cell surface area=0
WQ Output cell continuity=0
WQ Output cumulative cell continuity=0
WQ Output face conc=0
WQ Output face dconc_dx=0
WQ Output face courant=0
WQ Output face peclet=0
WQ Output face adv mass=0
WQ Output face disp mass=0
WQ Output cell mass=0
WQ Output cell source sink temp=0
WQ Output nsm pathways=0
WQ Output nsm derived pathways=0
WQ Create Restart=0
WQ Fixed Restart=0
WQ System Summary=0
WQ Write To DSS=0
Sorting and Armoring Iterations= 10
XS Update Threshold= 0.02
Bed Roughness Predictor= 0
Hydraulics Update Threshold= 0.02
Energy Slope Method= 1
Volume Change Method= 1
Sediment Retention Method= 0
Sediment TS Multiplier= 1
Warm Up Method= 0
XS Weighting Method= 0
Number of US Weighted Cross Sections= 1
Number of DS Weighted Cross Sections= 1
Upstream XS Weight=0
Main XS Weight=1
Downstream XS Weight=0
Number of DS XS's Weighted with US Boundary= 1
Upstream Boundary Weight= 1
Weight of XSs Associated with US Boundary= 0
Number of US XS's Weighted with DS Boundary= 1
Downstream Boundary Weight= 0.5
Weight of XSs Associated with DS Boundary= 0.5
Percentile Method= 0
Sediment Output Level= 3
Mass or Volume Output= 0
Output Increment Type= 1
Profile and TS Output Increment= 1
Transport Output Increment 1
XS Output Flag= 0
XS Output Increment= 10
Read HDF5 Sediment Hotstart= 0
Sediment Hotstart Type= 0
Write Gradation File= 0
Read Gradation Hotstart= 0
Write HDF5 File= 1
Write Binary Output= 1
Write DSS Sediment File= 0
DSS Sediment Output Type= 1
SV Curve= 0
Specific Gage Flag= 0
Subcell Erosion Methods= 0
Subcell Deposition Methods= 0
Advection Scheme= 1
Matrix Solver= 0
Implicit Weighting Factor= 1
Maximum Outer Loop Convergence Iterations= 5
Convergence Maximum Absolute= 0.001
Convergence RMSE= 0.0001
Grain Fractions Max Abs Error= 0.001
Max Subgrid Regions= 1
Max Subgrid Length Scale= 3.402823E+38
Initial Layer Thickness= 3.402823E+38
Min Layer Thickness= 3.402823E+38
Max Layer Thickness= 3.402823E+38
Number of Layers= 5

--- FRBEERN.f01 (steady flow) ---

Flow Title=Flow
Program Version=6.30
Number of Profiles= 1
Profile Names=F01pct
River Rch & RM=FRBEERN,Reach 1         ,598
     559
Boundary for River Rch & Prof#=FRBEERN,Reach 1         , 1
Up Type= 0
Dn Type= 3
Dn Slope=0.0343
DSS Import GetInterval= 0
DSS Import GetPeak= 0
DSS Import FillOption= 0

--- FRBEERN.g01 (geometry) ---

Geom Title=Geometry
Program Version=6.30

River Reach=FRBEERN         ,Reach 1
Reach XY= 29
1615080.82850248429327.1645311421615079.74334716429318.917350723
 1615074.7516327429294.8269026571615068.67476292429275.077075864
1615061.29570675429263.1403673631615037.52079631429235.781242608
1614992.73398712429193.6611534891614959.39039435429166.867195013
1614913.84066494429141.8595004361614881.68791477   429126.080836
1614861.44359059429121.615176254 1614845.9626368429126.378546649
1614831.21742836429137.6136879451614800.85094209 429165.59848902
1614773.85172026 429177.209204361614756.33858483429182.868919892
1614742.98196573  429186.40895321614730.73889537429185.359700488
1614722.02116328429181.9002829931614710.64461522429177.804625659
1614691.81742291429169.5638003831614686.23182621429168.133887628
1614681.06737211429167.5025974291614672.91576368429167.821094213
1614670.14530772429167.5529855721614666.74926493429166.569920553
 1614662.7276353429164.5144209681614656.31196837429160.755751124
1614607.39898509429140.355573924

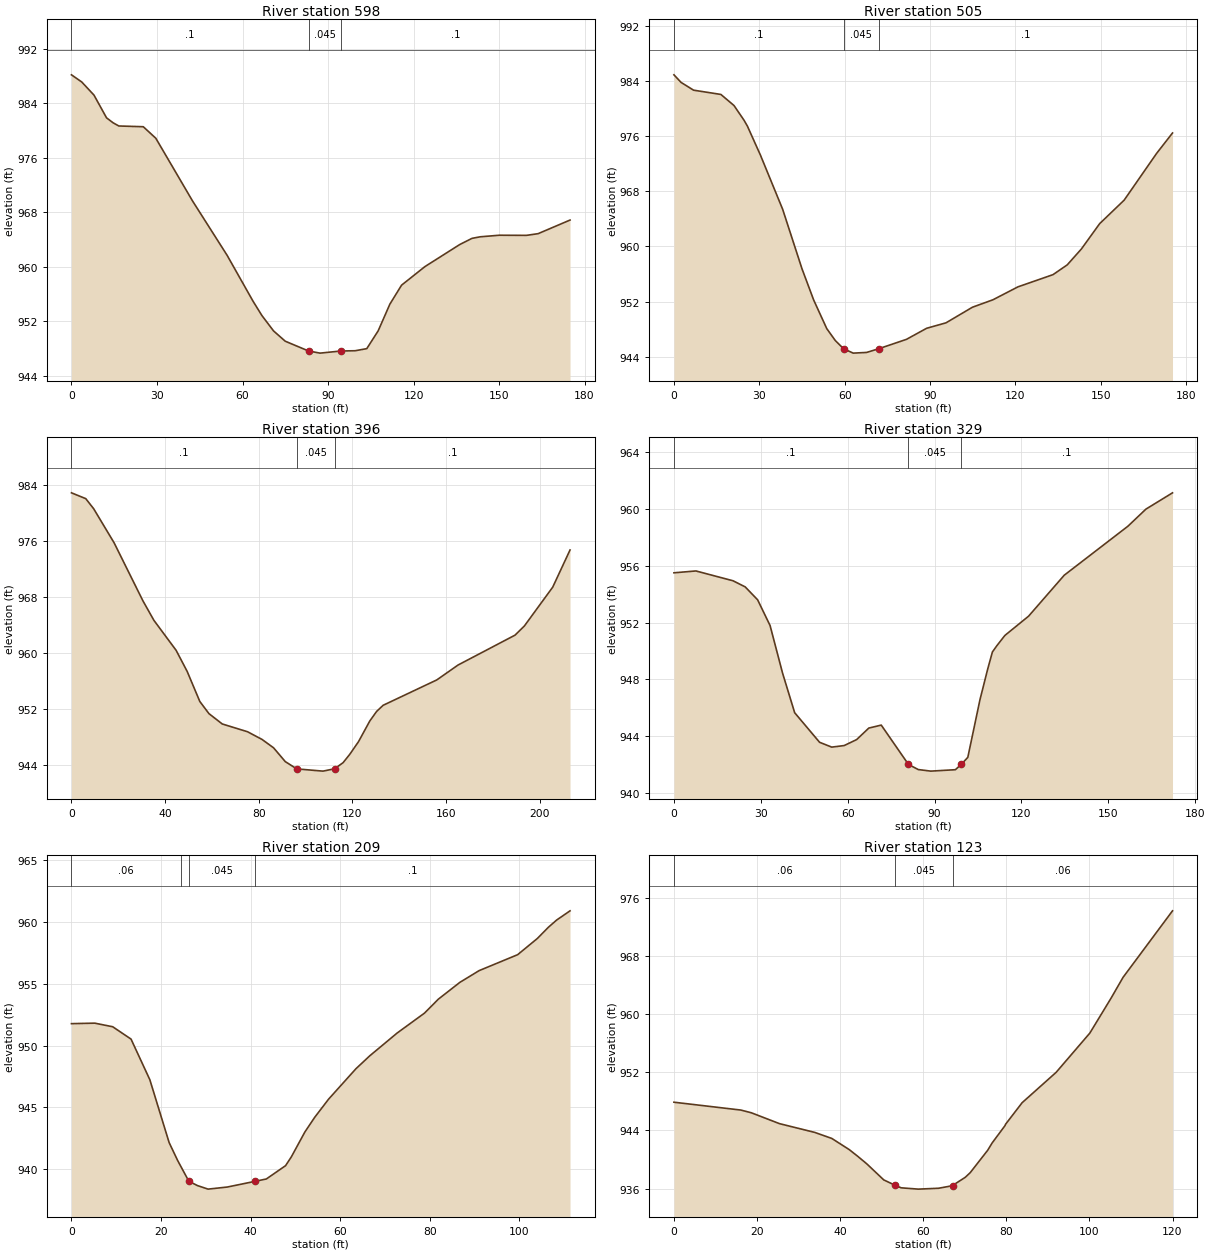
Type RM Length L Ch R = 1 ,598     ,94.7,92.3,90.8
XS GIS Cut Line= 4
1615167.46237309 429300.798578481615130.94145878429315.757924352
1615034.78150541429335.0953921241615003.13837633429354.960245381
#Sta/Elev= 30
       0   988.2     3.6  987.15     7.9  985.22    12.3  981.88    14.6  981.15
    16.6  980.68    25.2  980.57    29.6  978.87    42.5  969.64    54.6  961.67
    63.7  954.92    66.8  952.82    70.9  950.55      75  949.04    83.2   947.6
    87.2  947.29   94.65947.6061    99.5  947.64   103.6  947.95   107.6  950.57
   111.7  954.49   115.8  957.28     124  960.01   136.2  963.25   140.5  964.16
   143.4  964.39   150.1  964.62   159.6   964.6   163.7  964.85   174.9  966.85
#Mann= 3 ,0,0
       0      .1       0    83.2    .045       0   94.65      .1       0
Bank Sta=83.2,94.65
XS Rating Curve= 0 ,0
Exp/Cntr(USF)=0,0
Exp/Cntr=0.3,0.1

Type RM Length L Ch R = 1 ,505     ,112.3,109.2,107.1
XS GIS Cut Line= 3
1615102.28192417429208.9969165841614992.38626458429274.419750723
1614954.52923134429302.720639648
#Sta/Elev= 30
       0  984.93     2.5  983.83     6.9   982.7    16.5  982.08    21.1  980.47
    24.6  978.35    25.8  977.49    30.4  973.26    38.2   965.4      45  956.75
    49.1  952.22    53.7  948.06    56.7  946.33    59.6  945.14      63   944.5
    67.7   944.6   71.97945.1392    81.7   946.5    88.8  948.11    95.6   948.9
   104.9  951.17   112.1  952.25   120.9  954.13   133.2   955.9   138.2  957.32
   143.2  959.64   149.6  963.31   158.2  966.72   169.6  973.51   175.2  976.48
#Mann= 3 ,0,0
       0      .1       0    59.6    .045       0   71.97      .1       0
Bank Sta=59.6,71.97
XS Rating Curve= 0 ,0
Exp/Cntr(USF)=0,0
Exp/Cntr=0.3,0.1

Type RM Length L Ch R = 1 ,396     ,69.2,67,64.4
XS GIS Cut Line= 4
1615037.96172207429101.3065210621614993.48889661429129.239865976
1614928.43360649429218.1855168841614921.08272625429267.803958507
#Sta/Elev= 30
       0  982.83     6.1     982     9.5  980.55    18.2   975.7    30.5  967.42
    35.2  964.63    44.7  960.34    49.4  957.34    54.8  953.05    58.7  951.31
    64.4  949.83    75.2  948.72    81.4  947.62    86.3  946.43    91.3  944.46
    96.2  943.42   107.4   943.1  112.34943.4356     116  944.31   118.8  945.48
   122.6  947.32   127.4  950.26   130.3  951.62   133.1   952.5     156  956.12
   165.1  958.25   189.4  962.51   193.4  963.82   205.5  969.36   212.9  974.67
#Mann= 3 ,0,0
       0      .1       0    96.2    .045       0  112.34      .1       0
Bank Sta=96.2,112.34
XS Rating Curve= 0 ,0
Exp/Cntr(USF)=0,0
Exp/Cntr=0.3,0.1

Type RM Length L Ch R = 1 ,329     ,126.3,120.6,113.4
XS GIS Cut Line= 3
1614936.33038019429053.4316897871614893.67712448429168.232473788
  1614888.232028429217.692100097
#Sta/Elev= 30
       0  955.51     7.6  955.64    20.4  954.95    24.6  954.52    28.9  953.61
    33.2   951.8    37.5  948.46    41.7  945.66    50.3  943.58    54.5  943.24
    58.8  943.35    63.1  943.77    67.3  944.58    71.6  944.79      81  942.02
    84.4  941.66    88.7  941.55    97.2  941.65    99.2 942.018   101.5  942.52
   105.7  946.58   108.4  948.76     110  949.94   111.5  950.37   114.3   951.1
   122.5  952.46   134.8  955.34   156.8  958.79     163  959.99   172.2  961.14
#Mann= 3 ,-1,0
       0      .1       0      81    .045       0    99.2      .1       0
Bank Sta=81,99.2
XS Rating Curve= 0 ,0
Exp/Cntr(USF)=0,0
Exp/Cntr=0.3,0.1

Type RM Length L Ch R = 1 ,209     ,80.8,85.8,90.1
XS GIS Cut Line= 4
1614793.42403938429131.3437259651614794.89421543429145.677942433
 1614815.4766801429195.6639280681614831.64861663429235.358681366
#Sta/Elev= 30
       0  951.77     5.2  951.81     9.2  951.52    13.3  950.52    17.5  947.23
    21.8  942.15    23.7   940.7    26.2  939.02    28.1  938.67    30.5  938.38
    34.8  938.55    40.9939.0043    43.5   939.2    47.8  940.28    49.1     941
    52.1     943    54.3  944.19    57.4  945.66    63.5  948.12    66.6  949.17
    72.7  951.01    78.8  952.62    81.9  953.75    86.7  955.11      91  956.06
    99.6  957.35     104  958.66   106.5  959.58   108.3  960.15   111.3   960.9
#Mann= 4 ,-1,0
       0     .06       0   24.41      .1       0    26.2    .045       0
    40.9      .1       0
Bank Sta=26.2,40.9
XS Rating Curve= 0 ,0
Exp/Cntr(USF)=0,0
Exp/Cntr=0.3,0.1

Type RM Length L Ch R = 1 ,123     ,47.9,53.7,57.2
BEGIN DESCRIPTION:
Structure XS 4
END DESCRIPTION:
XS GIS Cut Line= 4
1614755.30972399429140.0177650371614731.30685461429148.422966562
1614713.99280241429208.7128638621614717.96725424429240.320525124
#Sta/Elev= 28
       0  947.89    16.1  946.81    18.6  946.44    25.4  944.94    33.9  943.73
      38   942.9    42.2  941.36    44.3  940.41    46.4  939.41    50.5  937.19
    53.3936.4324    54.7   936.1    58.8  935.92    63.7  936.04    67.2  936.41
    67.6  936.62    70.1  937.54    71.3  938.18    75.5  941.26    76.6  942.29
    79.7  944.68    79.8  944.84    83.8  947.82      92  952.01   100.1  957.41
   105.2  962.21   108.1  965.09     120  974.25
#Mann= 3 ,0,0
       0     .06       0    53.3    .045       0    67.2     .06       0
Bank Sta=53.3,67.2
XS Rating Curve= 0 ,0
Exp/Cntr(USF)=0,0
Exp/Cntr=0.3,0.1

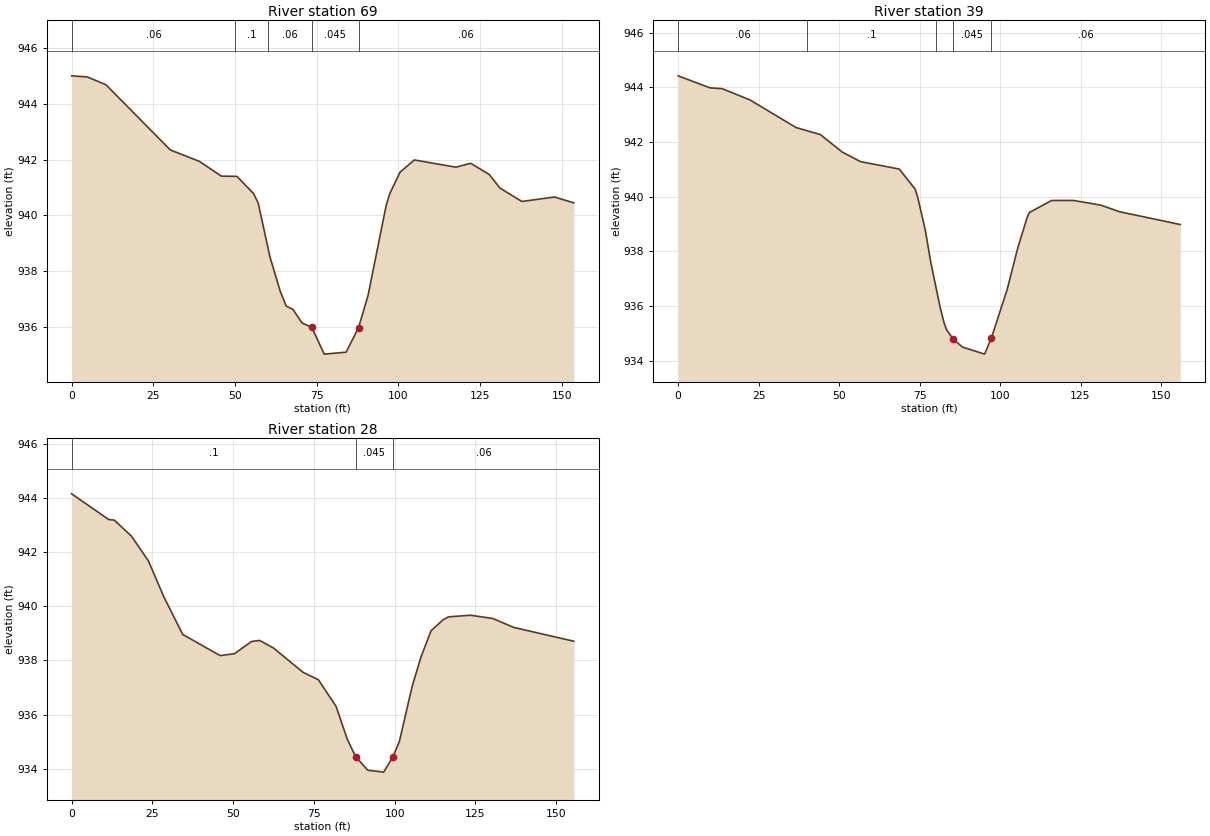
Type RM Length L Ch R = 1 ,69      ,29.7,29.5,28.8
BEGIN DESCRIPTION:
Structure XS 3
END DESCRIPTION:
XS GIS Cut Line= 2
1614736.91852938429118.6115580261614613.31089647429209.996437078
#Sta/Elev= 30
       0  945.01     4.8  944.97    10.5  944.69    30.2  942.35    39.1  941.94
    45.8  941.41    50.6   941.4    55.7  940.78    57.1  940.44    60.7  938.51
    63.8  937.29    65.7  936.74    67.7  936.63    70.5  936.14    73.5  935.98
    77.3  935.02      84  935.09    87.8  935.97    90.7  937.12    96.3  940.38
    97.4  940.79   100.5  941.55   104.9  941.99   117.6  941.73   122.1  941.87
   127.8  941.47   131.1  940.98   137.8   940.5   147.8  940.66   153.7  940.45
#Mann= 5 ,-1,0
       0     .06       0      50      .1       0      60     .06       0
    73.5    .045       0    87.8     .06       0
Bank Sta=73.5,87.8
XS Rating Curve= 0 ,0
Exp/Cntr(USF)=0,0
Exp/Cntr=0.3,0.1

Type RM Length L Ch R = 1 ,39      ,14.2,11.4,10.5
BEGIN DESCRIPTION:
Structure XS 2
END DESCRIPTION:
XS GIS Cut Line= 2
 1614720.1738001 429101.519322091614592.83535993429191.636414079
#Sta/Elev= 30
       0  944.42     9.9  943.98    13.7  943.95    22.3  943.54    36.6  942.53
    44.2  942.27      51  941.63    56.7  941.28    68.7  941.01    73.6  940.28
    73.9  940.18    74.5  939.94    76.8  938.77    78.5  937.59    81.4  935.95
    82.6  935.39    83.4  935.13    85.4   934.8    88.3   934.5    95.2  934.24
   97.29934.8192   102.2   936.6   105.5  938.12   108.4  939.23   109.1  939.42
     116  939.86   122.9  939.86   131.3  939.69   137.1  939.45     156  938.98
#Mann= 5 ,-1,0
       0     .06       0      40      .1       0      80     .06       0
    85.4    .045       0   97.29     .06       0
Bank Sta=85.4,97.29
XS Rating Curve= 0 ,0
Exp/Cntr(USF)=0,0
Exp/Cntr=0.3,0.1

Type RM Length L Ch R = 1 ,28      ,18.7,18.7,18.7
BEGIN DESCRIPTION:
Structure XS 1
END DESCRIPTION:
XS GIS Cut Line= 4
1614702.00623827429086.1792499781614642.19436759429138.640760966
1614621.68239788429167.5925448171614588.83788067429191.172845994
#Sta/Elev= 30
       0  944.15    11.5   943.2    13.2  943.18    18.5  942.59    23.8  941.67
    28.5  940.36    34.4  938.96      46  938.18    50.4  938.25    55.7   938.7
    58.2  938.74    62.5  938.46    71.7  937.56    76.4  937.29    81.9   936.3
    85.3  935.1187.89915934.4559    91.7  933.95    96.6  933.8899.48589934.4463
   101.5  935.02   105.4  937.03   108.2  938.14   111.3   939.1     115   939.5
   116.7  939.61   123.5  939.67   130.4  939.55   136.9  939.22   155.5  938.71
#Mann= 3 ,0,0
       0      .1       087.89915    .045       099.48589     .06       0
Bank Sta=87.89915,99.48589
XS Rating Curve= 0 ,0
Exp/Cntr(USF)=0,0
Exp/Cntr=0.3,0.1
LCMann Table=0

Chan Stop Cuts=-1
Use User Specified Reach Order=0
Composite Channel Slope=5